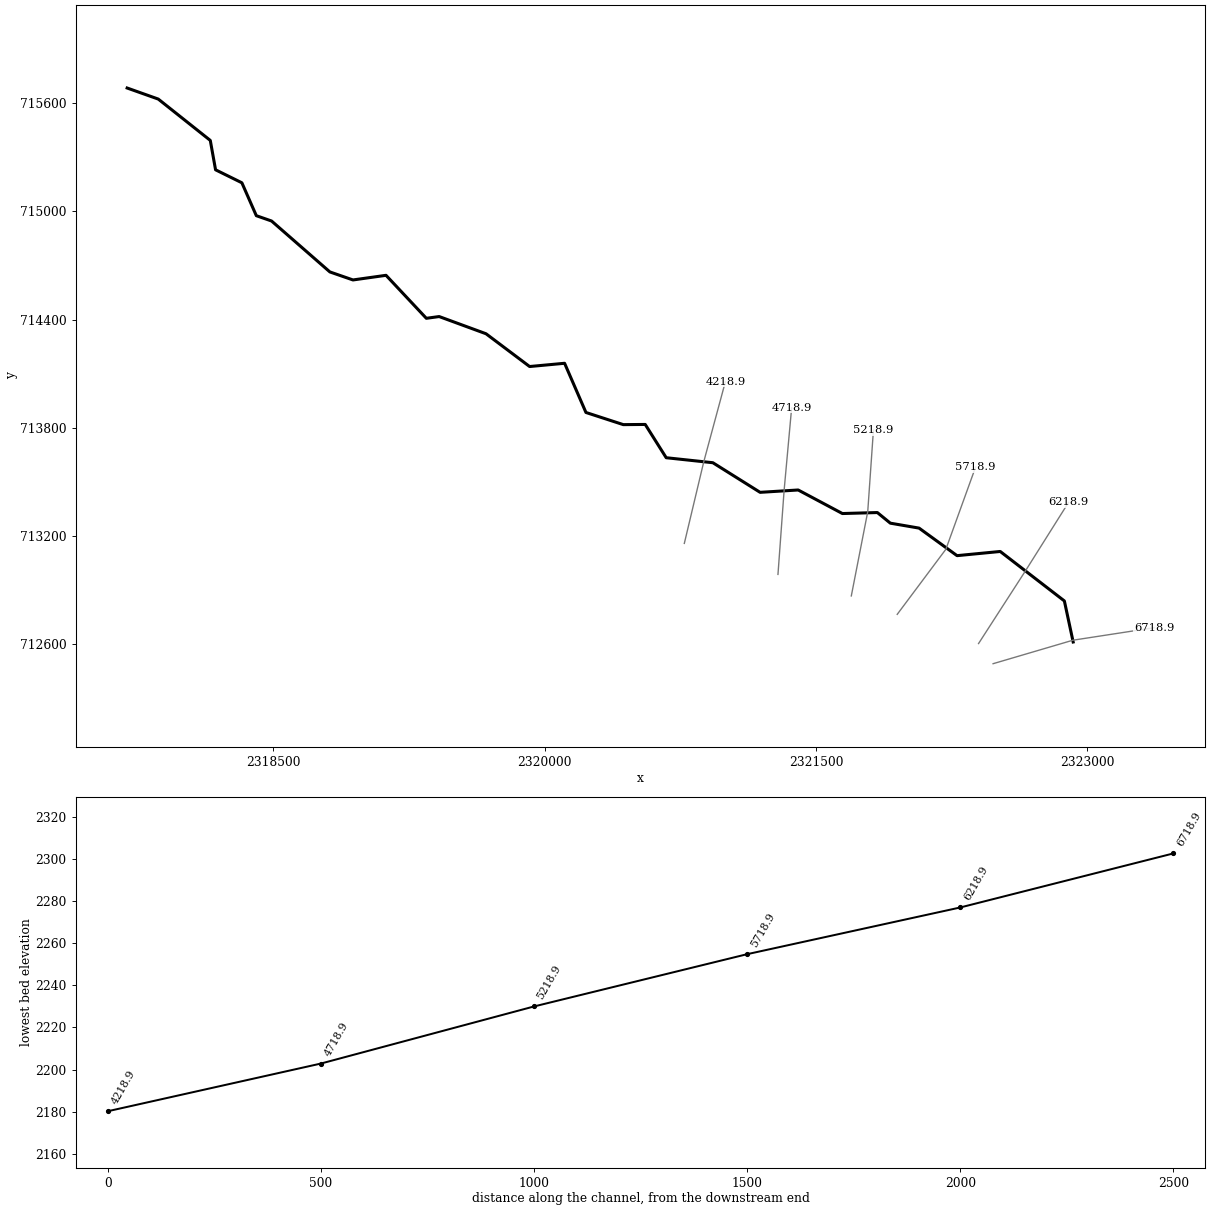
--- JOHNSRN.prj (project) ---

Proj Title=JOHNSRN
Current Plan=p01
Geom File=g01
Flow File=f01
Plan File=p01
DSS Export Rating Curves=0
DSS Export Rating Curve Sorted=0
DSS Export Volume Flow Curves=0
DXF OffsetX=0
DXF OffsetY=0
DXF ScaleX=0
DXF ScaleY=0

--- JOHNSRN.p01 (plan) ---

Plan Title=Floodplain
Program Version=4.00
Geom File=g01
Flow File=f01
K Sum by GR=0
Std Step Tol=0.01
Critical Tol=0.01
Num of Std Step Trials=20
Max Error Tol=0.3
Flow Tol Ratio=0.001
Split Flow NTrial=30
Split Flow Tol=0.02
Split Flow Ratio=0.02
Log Output Level=0
Friction Slope Method=1
Unsteady Friction Slope Method=2
Unsteady Bridges Friction Slope Method=1
Global Log Level=0
CheckData=False
Run HTab=0
Run UNet=0
Run PostProcess=0
UNET Theta=0
UNET Theta Warmup=0
UNET ZTol=0
UNET ZSATol=0
UNET MxIter=0
UNET MaxInSteps=0
UNET DtIC=0
UNET DtMin=0
UNET MaxCRTS=0
UNET WFStab=0
UNET SFStab=0
UNET WFX=0
UNET SFX=0
UNET DSS MLevel=0
UNET DZMax Abort=0
UNET Convert EG Bridges=0
UNET Use Existing IB Tables=0
UNET Froude Limit=0
UNET Froude Power=0
Write IC File=0
Echo Input=False
Echo Output=False
Write Detailed=0

--- JOHNSRN.f01 (steady flow) ---

Flow Title=Flow
Program Version=4.00
Number of Profiles=1
Profile Names=P100yr
River Rch & RM=JOHNSRN,Main      ,6718.9
339.0796
River Rch & RM=JOHNSRN,Main      ,5718.9
358.8952
River Rch & RM=JOHNSRN,Main      ,5718.9
355.1911
River Rch & RM=JOHNSRN,Main      ,5218.9
367.0577
River Rch & RM=JOHNSRN,Main      ,5218.9
364.2896
River Rch & RM=JOHNSRN,Main      ,4718.9
376.3076
River Rch & RM=JOHNSRN,Main      ,4218.9
384.2979
River Rch & RM=JOHNSRN,Main      ,4218.9
380.8380
Boundary for River Rch & Prof#=JOHNSRN,Main      ,1
Up Type=0
Dn Type=3
Dn Slope=0.049696

--- JOHNSRN.g01 (geometry) ---

Geom Title=Geometry
Program Version=4.00

River Reach=JOHNSRN     ,Main
Reach XY= 30
     2322922.147      712613.820     2322873.536      712841.250
     2322518.935      713115.382     2322280.133      713092.205
     2322070.237      713244.809     2321911.383      713272.153
     2321839.508      713331.007     2321646.279      713325.538
     2321401.748      713456.007     2321191.331      713442.986
     2320930.133      713607.049     2320672.147      713634.740
     2320556.175      713819.115     2320434.994      713818.073
     2320228.397      713885.434     2320110.342      714158.004
     2319916.939      714139.948     2319675.967      714321.545
     2319416.823      714416.858     2319345.989      714407.136
     2319123.073      714645.330     2318940.434      714619.635
     2318812.696      714664.029     2318490.387      714946.147
     2318406.012      714975.661     2318326.151      715157.953
     2318180.665      715229.828     2318151.498      715392.675
     2317863.824      715621.755     2317691.773      715682.994

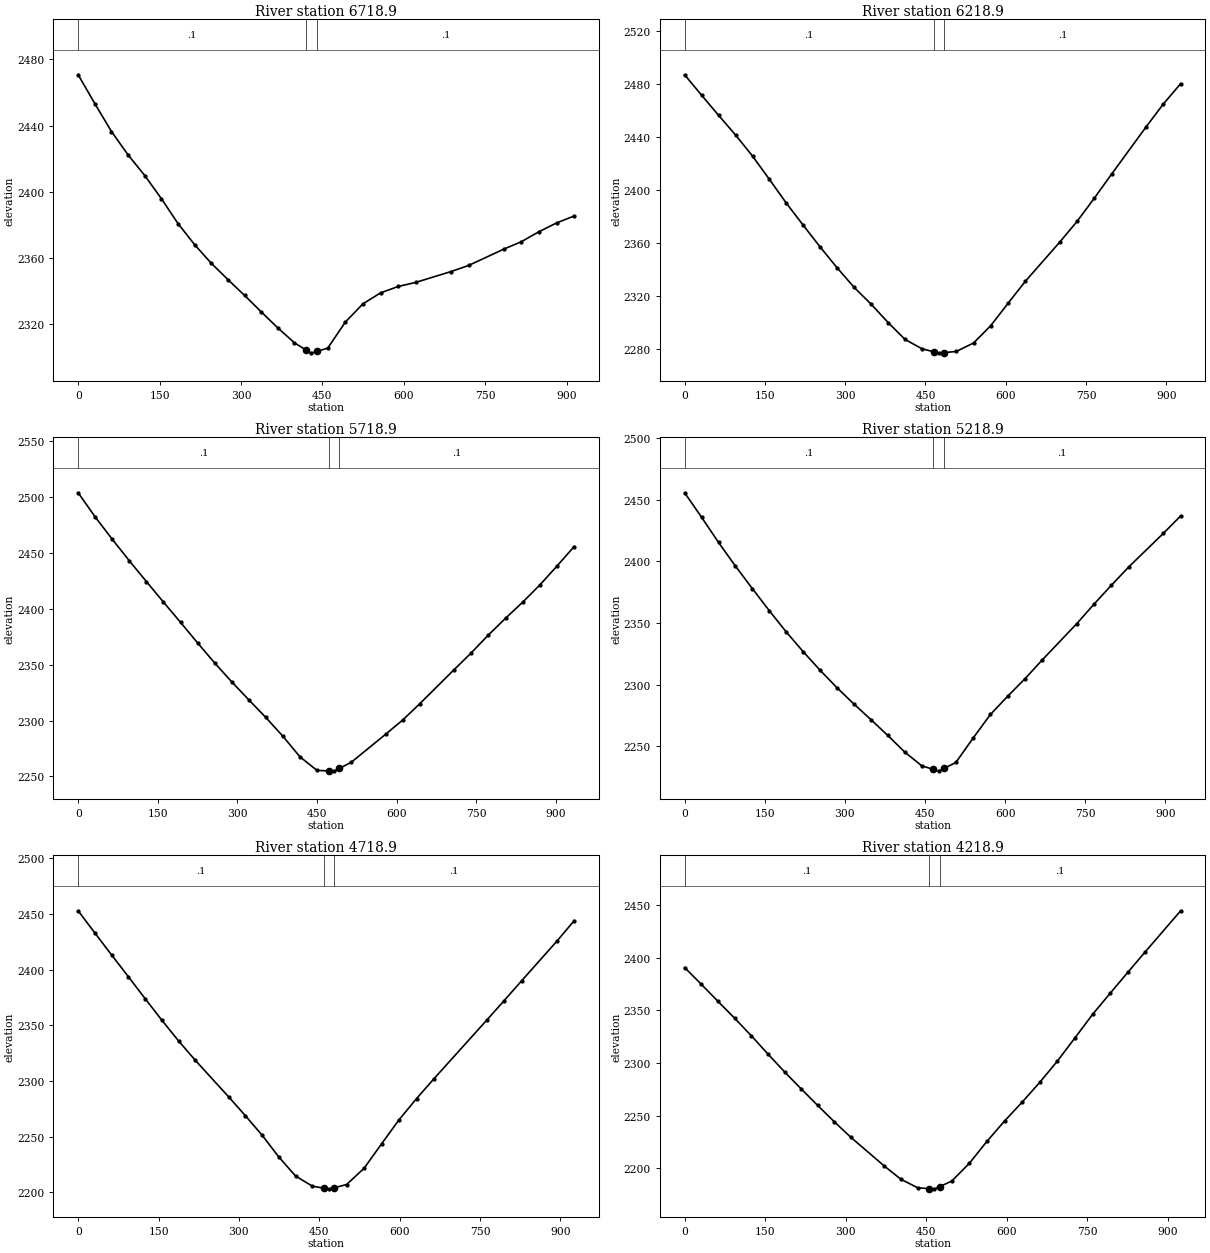
Type RM Length L Ch R = 1 ,6718.9,481.3,500,521
XS GIS Cut Line= 3
     2322479.417      712493.617     2322920.624      712623.703
     2323369.447      712692.864
#Sta/Elev= 30
       0 2470.60    30.7 2453.19    61.3 2436.37    92.0 2422.24   122.7 2409.79
   153.3 2395.84   184.0 2380.80   214.7 2368.03   245.3 2356.85   276.0 2346.98
   306.7 2337.42   337.3 2327.53   368.0 2317.82   398.6 2308.82   419.3 2304.63
   429.3 2302.61   439.3 2303.60   460.0 2305.65   492.4 2321.38   524.9 2332.38
   557.3 2338.98   589.7 2342.84   622.2 2345.31   687.0 2351.83   719.5 2355.52
   784.4 2365.39   816.8 2369.87   849.2 2375.90   881.7 2381.19   914.1 2385.40
#Mann= 3 , 0 , 0
       0     0.1       0   419.3   0.045       0   439.3     0.1       0
Bank Sta=419.3,439.3
Exp/Cntr=0.3,0.1

Type RM Length L Ch R = 1 ,6218.9,500.1,500,504.6
XS GIS Cut Line= 3
     2322399.071      712605.208     2322656.461      713004.888
     2322896.620      713387.209
#Sta/Elev= 30
       0 2487.09    31.7 2471.66    63.4 2456.49    95.1 2441.66   126.8 2425.75
   158.5 2408.06   190.2 2390.11   221.8 2373.38   253.5 2356.94   285.2 2341.24
   316.9 2326.54   348.6 2313.87   380.3 2300.02   412.0 2287.26   443.7 2280.21
   465.4 2277.99   475.4 2276.96   485.4 2277.35   507.6 2278.23   539.9 2284.61
   572.1 2297.73   604.4 2314.58   636.6 2331.15   701.1 2360.83   733.4 2376.45
   765.6 2393.94   797.9 2412.12   862.4 2447.80   894.6 2465.05   926.9 2480.39
#Mann= 3 , 0 , 0
       0     0.1       0   465.4   0.045       0   485.4     0.1       0
Bank Sta=465.4,485.4
Exp/Cntr=0.3,0.1

Type RM Length L Ch R = 1 ,5718.9,487.5,500,505
XS GIS Cut Line= 3
     2321949.450      712767.104     2322218.400      713127.620
     2322382.863      713583.412
#Sta/Elev= 30
       0 2503.74    32.1 2482.07    64.2 2462.15    96.4 2442.91   128.5 2424.33
   160.6 2405.99   192.8 2387.86   224.9 2369.48   257.0 2351.60   289.2 2334.65
   321.3 2318.62   353.4 2302.81   385.5 2286.05   417.7 2267.62   449.8 2255.44
   472.1 2254.99   482.1 2254.79   492.1 2257.24   514.4 2262.70   579.0 2287.73
   611.3 2300.51   643.6 2315.14   708.2 2345.58   740.5 2360.62   772.8 2376.57
   805.1 2391.58   837.4 2405.95   869.7 2421.32   902.0 2438.24   934.3 2455.72
#Mann= 3 , 0 , 0
       0     0.1       0   472.1   0.045       0   492.1     0.1       0
Bank Sta=472.1,492.1
Exp/Cntr=0.3,0.1

Type RM Length L Ch R = 1 ,5218.9,496.2,500,498.4
XS GIS Cut Line= 3
     2321695.518      712868.999     2321786.351      713335.577
     2321817.829      713787.578
#Sta/Elev= 30
       0 2455.45    31.7 2435.62    63.4 2415.26    95.1 2396.03   126.8 2377.81
   158.4 2359.95   190.1 2342.79   221.8 2326.79   253.5 2311.71   285.2 2297.51
   316.9 2284.32   348.6 2271.74   380.3 2258.86   412.0 2245.40   443.6 2234.38
   465.3 2231.37   475.3 2229.98   485.3 2232.15   507.7 2237.00   540.1 2256.83
   572.4 2275.90   604.8 2290.71   637.2 2304.89   669.5 2320.13   734.2 2349.55
   766.6 2365.42   799.0 2380.68   831.3 2395.39   896.1 2422.63   928.4 2436.69
#Mann= 3 , 0 , 0
       0     0.1       0   465.3   0.045       0   485.3     0.1       0
Bank Sta=465.3,485.3
Exp/Cntr=0.3,0.1

Type RM Length L Ch R = 1 ,4718.9,502.7,500,494.2
XS GIS Cut Line= 3
     2321290.068      712988.319     2321324.168      713455.362
     2321365.648      713910.866
#Sta/Elev= 28
       0 2452.78    31.2 2432.80    62.4 2413.10    93.7 2393.59   124.9 2373.94
   156.1 2354.58   187.3 2335.98   218.5 2318.60   281.0 2285.63   312.2 2268.71
   343.4 2251.23   374.6 2231.65   405.8 2214.61   437.1 2205.55   458.3 2203.74
   468.3 2202.88   478.3 2204.15   501.0 2207.02   533.6 2221.61   566.3 2243.59
   599.0 2265.25   631.6 2284.20   664.3 2302.16   762.3 2354.48   795.0 2372.14
   827.7 2389.98   893.0 2425.29   925.7 2443.89
#Mann= 3 , 0 , 0
       0     0.1       0   458.3   0.045       0   478.3     0.1       0
Bank Sta=458.3,478.3
Exp/Cntr=0.3,0.1

Type RM Length L Ch R = 1 ,4218.9,4209.9,4218.9,4207.1
XS GIS Cut Line= 3
     2320772.291      713160.096     2320879.811      713612.387
     2320999.298      714055.781
#Sta/Elev= 30
       0 2390.61    31.0 2374.72    62.0 2358.57    93.0 2342.56   124.0 2325.96
   155.0 2308.62   186.0 2291.63   217.0 2275.47   247.9 2259.66   278.9 2244.16
   309.9 2229.33   371.9 2202.21   402.9 2189.63   433.9 2181.60   454.9 2180.69
   464.9 2180.25   474.9 2182.58   497.7 2187.88   530.5 2204.80   563.3 2225.68
   596.1 2244.94   628.9 2262.88   661.7 2281.66   694.5 2301.83   727.3 2323.89
   760.1 2346.20   792.9 2366.25   825.7 2386.07   858.5 2405.71   924.1 2444.47
#Mann= 3 , 0 , 0
       0     0.1       0   454.9   0.045       0   474.9     0.1       0
Bank Sta=454.9,474.9
Exp/Cntr=0.3,0.1